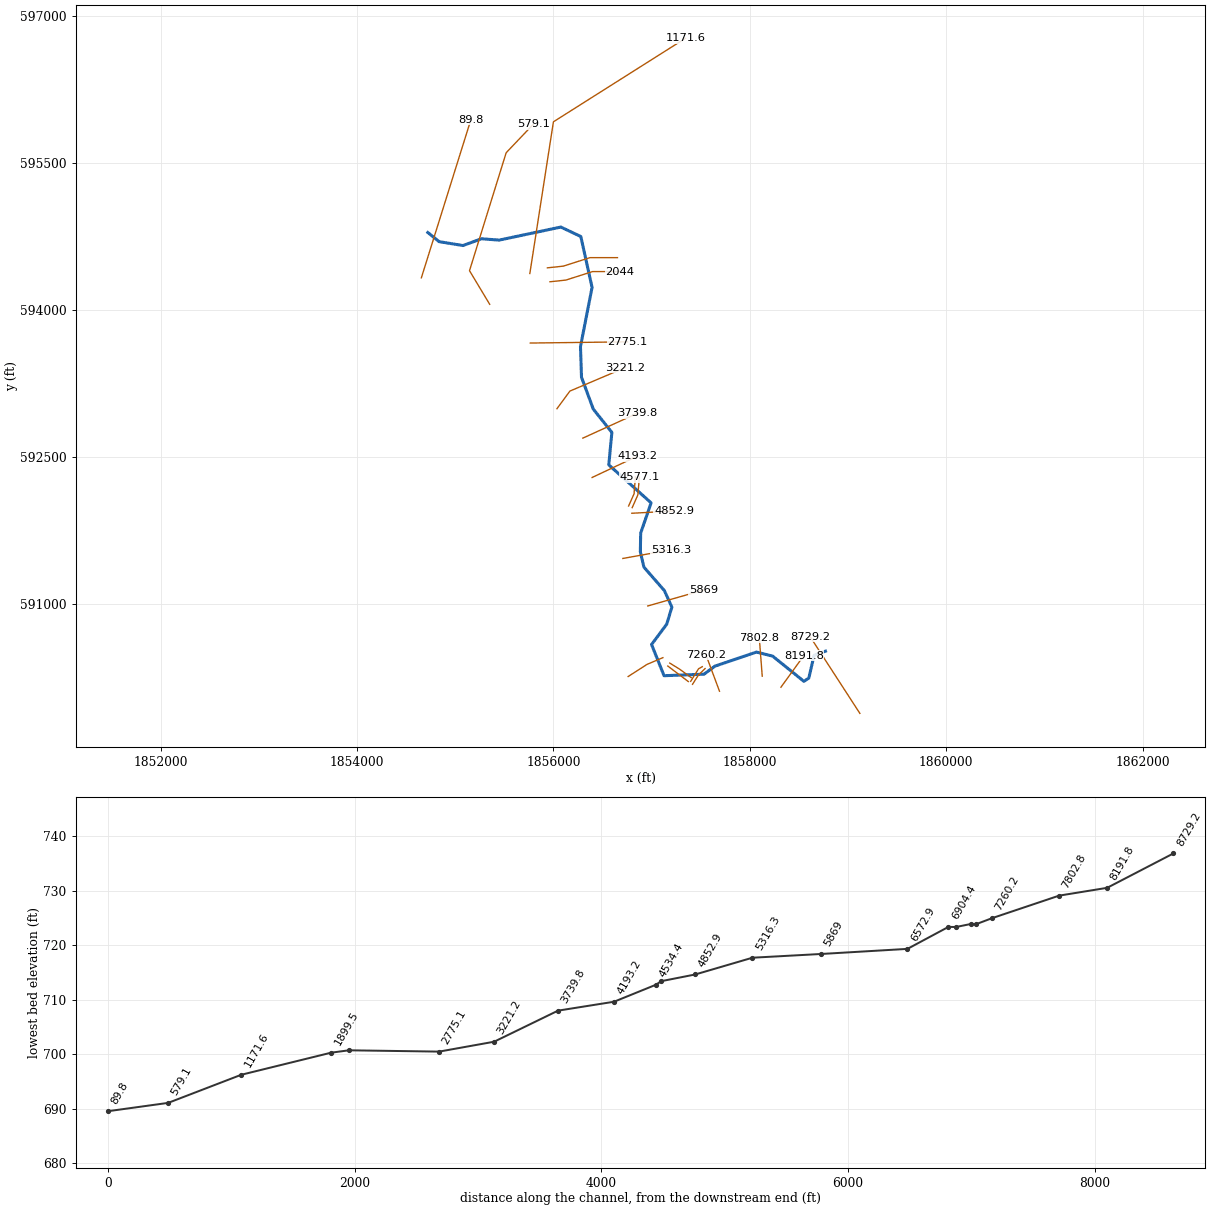
--- McCownCrk.prj (project) ---

Proj Title=McCownCrk
Current Plan=p01
Default Exp/Contr=0,0
English Units
Geom File=g01
Flow File=f01
Plan File=p01
BEGIN DESCRIPTION:
AMEC Environment & Infrastructure, 2013
Projection: NAD 1983 State Plane West Virginia South FIPS 4702 (US Feet)
Vertical Datum: NAVD 1988
END DESCRIPTION:
DSS Export Rating Curves= 0
DSS Export Rating Curve Sorted= 0
DSS Export Volume Flow Curves= 0
DXF OffsetX= 0
DXF OffsetY= 0
DXF ScaleX= 0
DXF ScaleY= 0

--- McCownCrk.p01 (plan) ---

Plan Title=Floodplain
Program Version=4.00
Geom File=g01
Flow File=f01
K Sum by GR=0
Std Step Tol=0.01
Critical Tol=0.01
Num of Std Step Trials=20
Max Error Tol=0.3
Flow Tol Ratio=0.001
Split Flow NTrial=30
Split Flow Tol=0.02
Split Flow Ratio=0.02
Log Output Level=0
Friction Slope Method=1
Unsteady Friction Slope Method=2
Unsteady Bridges Friction Slope Method=1
Global Log Level=0
CheckData=False
Run HTab=0
Run UNet=0
Run PostProcess=0
UNET Theta=0
UNET Theta Warmup=0
UNET ZTol=0
UNET ZSATol=0
UNET MxIter=0
UNET MaxInSteps=0
UNET DtIC=0
UNET DtMin=0
UNET MaxCRTS=0
UNET WFStab=0
UNET SFStab=0
UNET WFX=0
UNET SFX=0
UNET DSS MLevel=0
UNET DZMax Abort=0
UNET Convert EG Bridges=0
UNET Use Existing IB Tables=0
UNET Froude Limit=0
UNET Froude Power=0
Write IC File=0
Echo Input=False
Echo Output=False
Write Detailed=0

--- McCownCrk.f01 (steady flow) ---

Flow Title=NFF Regression Equation
Program Version=4.00
Number of Profiles=1
Profile Names=P100yr
River Rch & RM=McCownCrk,Main      ,8729.2
1018.951
River Rch & RM=McCownCrk,Main      ,6572.9
1303.333
River Rch & RM=McCownCrk,Main      ,5316.3
1337.951
River Rch & RM=McCownCrk,Main      ,2044
1460.589
River Rch & RM=McCownCrk,Main      ,579.1
1619.011
River Rch & RM=McCownCrk,Main      ,89.8
1621.251
Boundary for River Rch & Prof#=McCownCrk,Main      ,1
Up Type=0
Dn Type=3
Dn Slope=0.005952

--- McCownCrk.g01 (geometry) ---

Geom Title=USGS 3m DEM
Program Version=4.10

River Reach=McCownCrk       ,Main
Reach XY= 30
     1858770.568      590516.284     1858654.417      590474.087
     1858600.589      590241.366     1858550.226      590208.367
     1858232.399      590465.386      1858067.41      590507.061
     1857643.661      590362.897     1857533.383      590281.268
     1857126.127      590265.621     1856998.934      590584.099
     1857153.081      590790.968     1857205.987      590965.515
     1857129.566      591133.972     1856921.151      591373.629
     1856884.674      591529.931     1856888.139      591720.968
     1856994.066      592030.105     1856563.347      592417.373
     1856594.594      592749.084     1856405.284      592987.005
     1856285.438      593311.763     1856275.005       593624.37
     1856393.075      594228.748     1856278.431      594748.018
     1856075.051      594844.692     1855446.551      594711.512
     1855265.933      594725.398     1855078.372      594655.921
     1854835.232      594695.855     1854720.382       594788.97

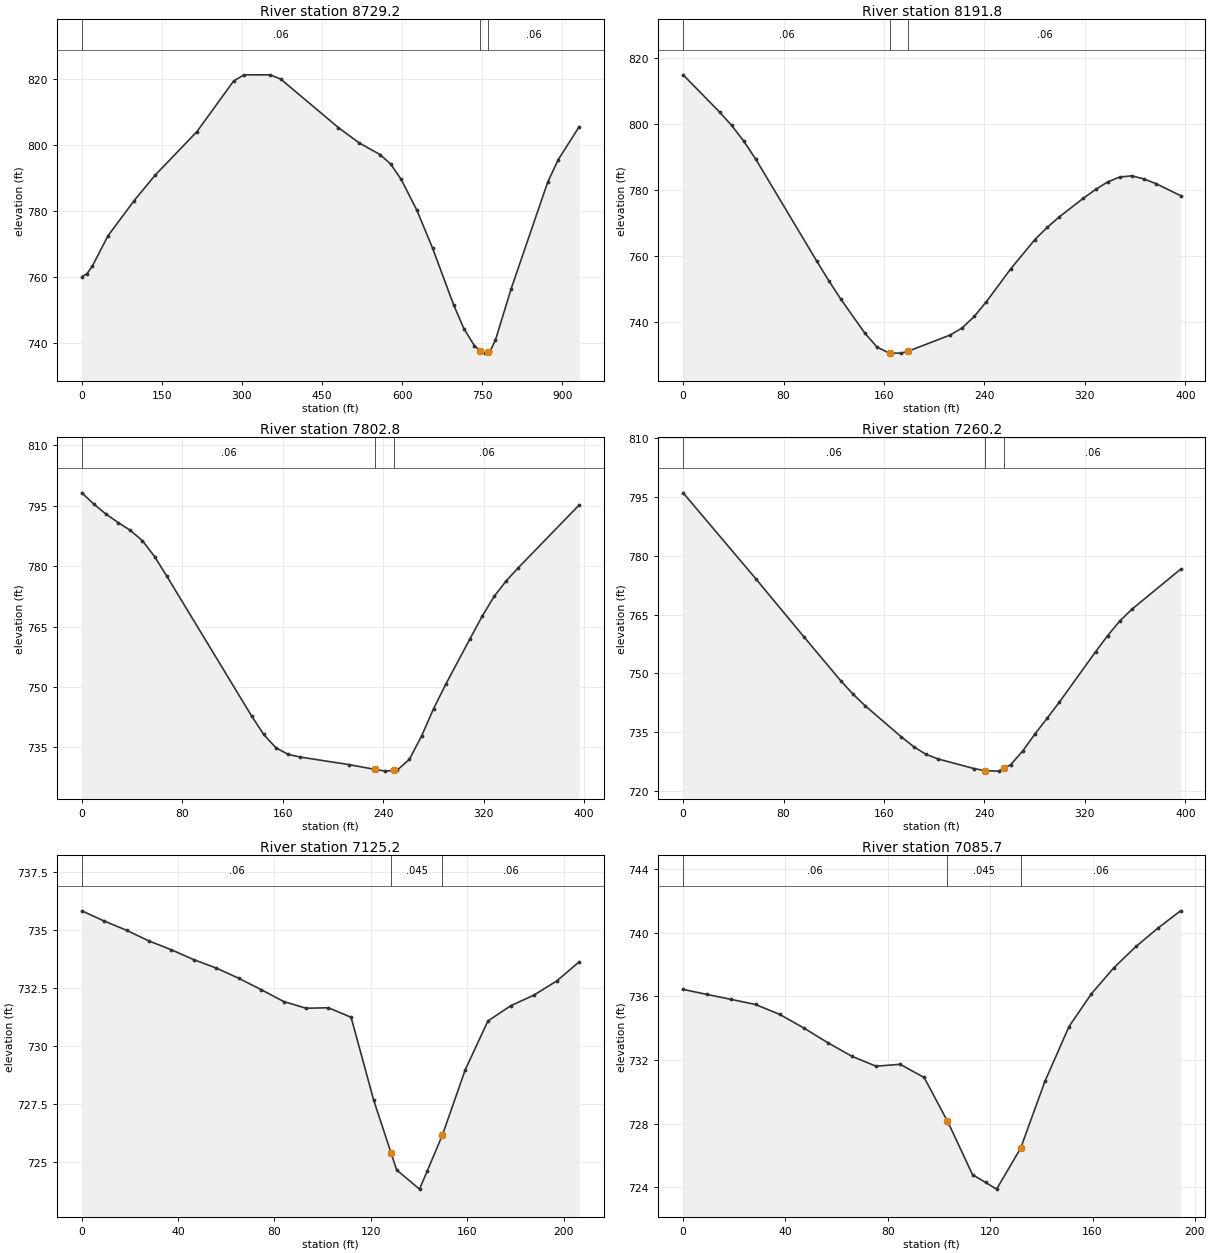
Type RM Length L Ch R = 1 ,8729.2  ,564.9,537.5,510.1
XS GIS Cut Line= 2
     1859120.477      589881.255     1858614.386      590663.395
#Sta/Elev= 30
       0  759.98     9.8   760.9    19.6  763.14      49  772.36    98.1  783.04
   137.3  790.74   215.7  803.96   284.4  819.29     304  821.16     353  821.15
   372.6  819.88   480.5  805.18   519.7  800.51     559  796.96   578.6  794.11
   598.2  789.47   627.6  780.12     657  768.63   696.2  751.54   715.9  744.14
   735.5  739.05   745.1  737.61   755.1  736.82   760.1  737.17   764.9  737.51
   774.7  740.75   804.1   756.3   872.8  788.72   892.4  795.47   931.6  805.46
#Mann= 3 , 0 , 0
       0     .06       0   745.1    .045       0   760.1     .06       0
Bank Sta=745.1,760.1
XS Rating Curve= 0 ,0
Exp/Cntr=0.3,0.1

Type RM Length L Ch R = 1 ,8191.8  ,372.9,388.8,404.7
XS GIS Cut Line= 2
     1858316.371      590147.886     1858548.484       590468.92
#Sta/Elev= 30
       0  814.78      29  803.53    38.6  799.48    48.3   794.7      58  789.15
   106.3  758.45     116  752.45   125.6  746.86   144.9  736.48   154.6  732.29
   164.3  730.51   164.5  730.51   173.9  730.52   179.5  731.12   212.6  735.98
   222.2  738.14   231.9  741.62   241.6  746.11   260.9  756.01   280.2   764.9
   289.9  768.56   299.5  771.73   318.9  777.44   328.5  780.06   338.2  782.36
   347.8  783.84   357.5   784.2   367.2  783.24   376.8   781.8   396.2  778.19
#Mann= 3 , 0 , 0
       0     .06       0   164.5    .045       0   179.5     .06       0
Bank Sta=164.5,179.5
XS Rating Curve= 0 ,0
Exp/Cntr=0.3,0.1

Type RM Length L Ch R = 1 ,7802.8  ,537.1,542.5,547.9
XS GIS Cut Line= 2
     1858126.199      590260.428     1858095.975       590655.43
#Sta/Elev= 28
       0  798.23     9.7  795.41    19.3  792.94      29  790.84    38.6  788.92
    48.3  786.34      58  782.39    67.6  777.59   135.3  742.76   144.9  738.19
   154.6  734.89   164.3  733.25   173.9  732.58   212.6  730.71   233.7   729.5
   241.6  729.08   248.7  729.27   251.2  729.34   260.9  731.99   270.6  737.77
   280.2   744.6   289.9  750.66   309.2  761.96   318.9  767.56   328.5  772.52
   338.2   776.4   347.8  779.65   396.2  795.22
#Mann= 3 , 0 , 0
       0     .06       0   233.7    .045       0   248.7     .06       0
Bank Sta=233.7,248.7
XS Rating Curve= 0 ,0
Exp/Cntr=0.3,0.1

Type RM Length L Ch R = 1 ,7260.2  ,160.6,134.7,108.7
XS GIS Cut Line= 2
     1857690.753       590107.23     1857553.055      590478.685
#Sta/Elev= 24
       0  796.11      58   774.1    96.6  759.14   125.6  748.04   135.3  744.66
   144.9   741.7   173.9  733.69   183.6  731.23   193.2  729.29   202.9  728.09
   231.9   725.6   240.8  725.06   251.2  724.96   255.8  725.74   260.9  726.61
   270.6  730.14   280.2  734.46   289.9  738.46   299.5  742.52   328.5  755.47
   338.2  759.63   347.8  763.33   357.5  766.36   396.2  776.57
#Mann= 3 , 0 , 0
       0     .06       0   240.8    .045       0   255.8     .06       0
Bank Sta=240.8,255.8
XS Rating Curve= 0 ,0
Exp/Cntr=0.3,0.1

Type RM Length L Ch R = 1 ,7125.2  ,33.4,39.5,45.7
XS GIS Cut Line= 3
       1857416.2      590177.918     1857475.866      590272.412
     1857544.028      590338.276
#Sta/Elev= 25
       0  735.81     9.3  735.37    18.6  734.97    27.9  734.51    37.2  734.13
    46.6   733.7    55.9  733.34    65.2   732.9    74.5  732.41    83.8   731.9
    93.1  731.61   102.4  731.63   111.8  731.22   121.2  727.64   128.4  725.37
   130.7  724.64   140.2  723.81   143.4  724.59   149.7  726.14   159.2  728.96
   168.6  731.06   178.1  731.72   187.6  732.17   197.1  732.78   206.5  733.61
#Mann= 3 , 0 , 0
       0     .06       0   128.4    .045       0   149.7     .06       0
Bank Sta=128.4,149.7
XS Rating Curve= 0 ,0
Exp/Cntr=0.3,0.1

Type RM Length L Ch R = 1 ,7085.7  ,81.3,118.3,155.4
XS GIS Cut Line= 3
      1857397.66      590208.609     1857477.509      590336.505
     1857515.737      590357.594
#Sta/Elev= 24
       0  736.44     9.4  736.12    18.8  735.81    28.3  735.49    37.7  734.87
    47.1  734.02    56.5  733.09      66  732.23    75.4  731.61    84.8  731.73
    94.2   730.9   103.2  728.18   103.7  728.03   113.1  724.79   118.2   724.3
   122.5  723.88   131.9  726.45   141.4  730.66   150.8   734.1   159.5  736.15
   168.2  737.78     177  739.14   185.7  740.31   194.4  741.38
#Mann= 3 , 0 , 0
       0     .06       0   103.2    .045       0   131.9     .06       0
Bank Sta=103.2,131.9
XS Rating Curve= 0 ,0
Exp/Cntr=0.3,0.1

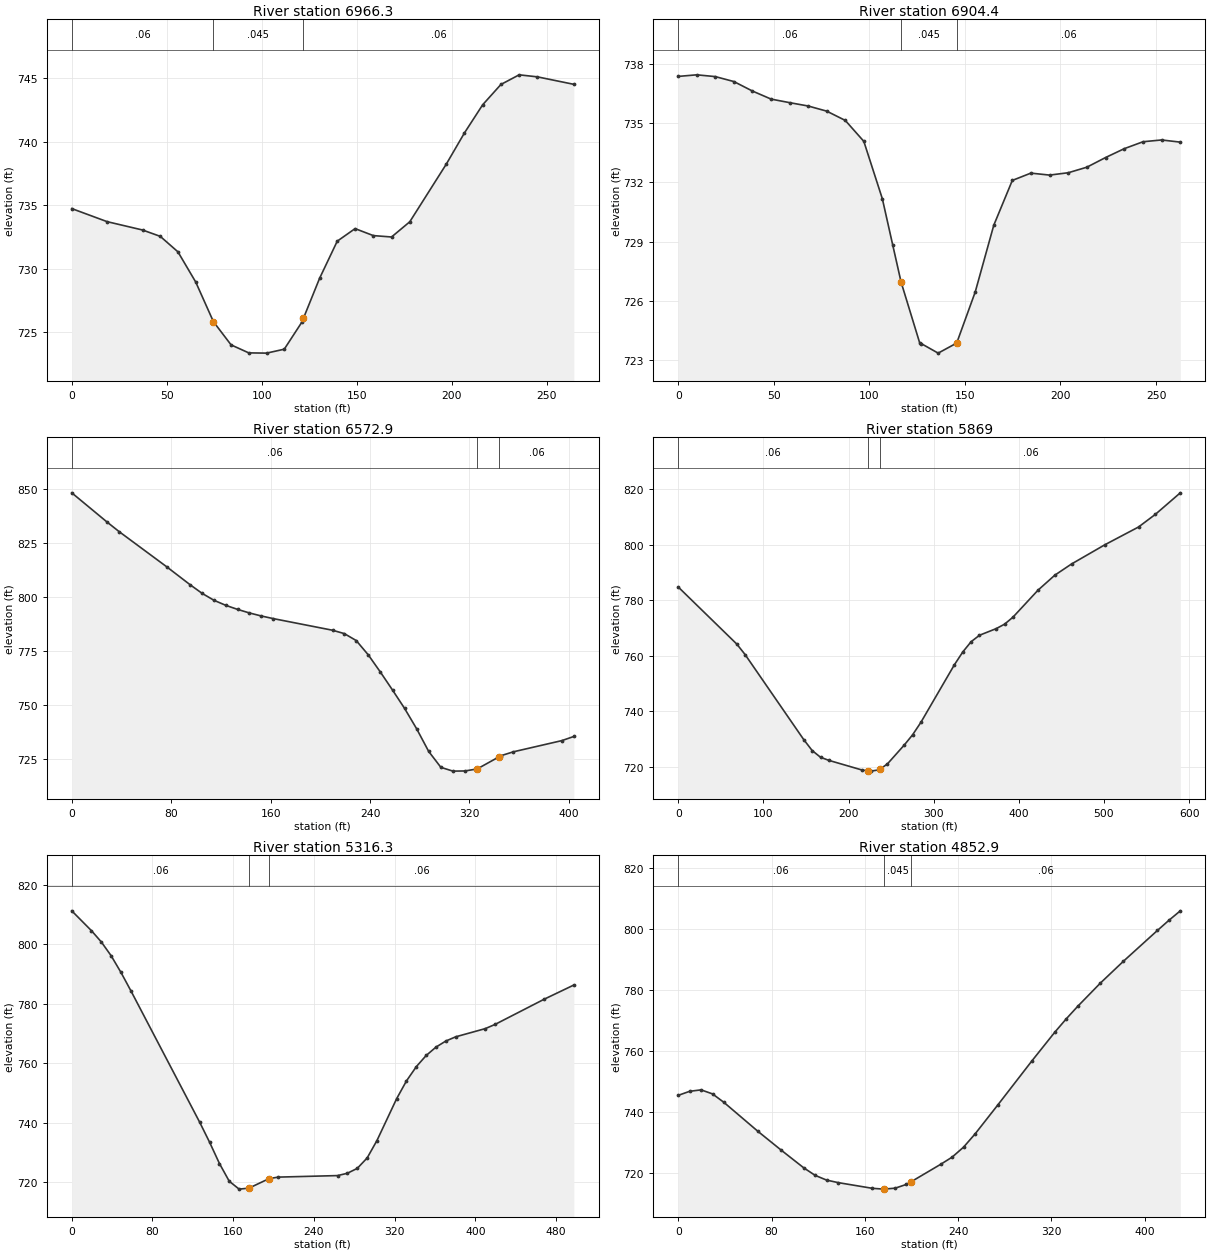
Type RM Length L Ch R = 1 ,6966.3  ,62.7,62,61.2
XS GIS Cut Line= 3
     1857402.877      590246.244      1857282.35      590334.128
     1857184.231      590394.509
#Sta/Elev= 26
       0  734.73    18.6   733.7    37.3  733.04    46.6  732.54    55.9  731.32
    65.3  728.93    74.6  725.81    83.9  723.98    93.2  723.35   102.6  723.33
   111.9  723.64   121.2  725.78     122 726.077   130.5  729.23   139.8  732.16
   149.2  733.15   158.8   732.6   168.4  732.49     178  733.69   197.2  738.23
   206.8   740.7   216.4  742.92     226  744.52   235.6  745.28   245.2  745.12
   264.4  744.53
#Mann= 3 , 0 , 0
       0     .06       0    74.6    .045       0     122     .06       0
Bank Sta=74.6,122
XS Rating Curve= 0 ,0
Exp/Cntr=0.3,0.1

Type RM Length L Ch R = 1 ,6904.4  ,382.8,332.3,281.8
XS GIS Cut Line= 3
     1857373.419      590205.844     1857226.429      590317.409
     1857164.114      590364.617
#Sta/Elev= 30
       0  737.37     9.7  737.45    19.4  737.36    29.1  737.11    38.8  736.63
    48.6  736.22    58.3  736.04      68  735.87    77.7  735.61    87.4  735.14
    97.1  734.08   106.8  731.17   112.2  728.84   116.6  726.95   126.3  723.88
   127.2  723.83     136  723.35   145.7  723.86   155.4  726.45   165.1  729.83
   174.8   732.1   184.5  732.47   194.3  732.37   204.1  732.49   213.8  732.77
   223.6  733.26   233.4  733.71   243.2  734.06   252.9  734.15   262.7  734.04
#Mann= 3 , 0 , 0
       0     .06       0   116.6    .045       0   145.7     .06       0
Bank Sta=116.6,145.7
XS Rating Curve= 0 ,0
Exp/Cntr=0.3,0.1

Type RM Length L Ch R = 1 ,6572.9  ,706.5,703.7,700.9
XS GIS Cut Line= 3
     1856760.666       590257.53     1856953.135      590381.367
     1857114.272      590449.999
#Sta/Elev= 30
       0  848.42    28.6  834.77    38.1  830.43    76.3  814.15    95.4  805.71
   104.9  801.78   114.4  798.58     124  796.21   133.5  794.33     143  792.69
   152.6  791.28   162.1  790.08   209.8  784.68   219.3  783.12   228.9  779.89
   238.6  773.24   248.3   765.3   258.1  756.93   267.8  748.42   277.5  738.97
   287.2  728.46     297  721.08   306.7  719.32   316.4   719.4   326.2  720.33
   343.6  725.89   345.6  726.52   355.4  728.29   394.3  733.47     404   735.4
#Mann= 3 , 0 , 0
       0     .06       0   326.2    .045       0   343.6     .06       0
Bank Sta=326.2,343.6
XS Rating Curve= 0 ,0
Exp/Cntr=0.3,0.1

Type RM Length L Ch R = 1 ,5869    ,554.6,552.3,550
XS GIS Cut Line= 2
      1856960.27       590977.45     1857527.296      591139.457
#Sta/Elev= 30
       0  784.73    68.8  764.16    78.6  760.36   147.4  729.74   157.3   725.8
   167.1  723.38   176.9  722.26   216.2  718.75   222.5  718.51   226.1  718.38
   235.9  718.84   237.5  719.19   245.7  720.98   265.4  727.76   275.2  731.44
     285  735.96   324.3  756.68   334.2  761.32     344  765.02   353.8  767.34
   373.5  769.74   383.3  771.34   393.1  773.85   422.6   783.6   442.3  788.99
   461.9  793.02   501.3  799.99   540.6  806.35   560.2  810.86   589.7  818.67
#Mann= 3 , 0 , 0
       0     .06       0   222.5    .045       0   237.5     .06       0
Bank Sta=222.5,237.5
XS Rating Curve= 0 ,0
Exp/Cntr=0.3,0.1

Type RM Length L Ch R = 1 ,5316.3  ,465.7,463.4,461
XS GIS Cut Line= 2
     1856706.501      591462.364      1857196.32      591550.645
#Sta/Elev= 30
       0  811.21    19.5  804.54    29.3  800.75      39  796.13    48.8   790.5
    58.6  784.34   126.9  740.11   136.6  733.47   146.4   726.3   156.1  720.35
   165.9   717.7   175.7  718.04   195.7  721.25   204.9  721.74   263.5  722.25
   273.2  723.03     283  724.67   292.8  728.17   302.5  734.01     322  748.06
   331.8  754.07   341.6  758.87   351.3   762.6   361.1  765.43   370.8  767.46
   380.6  768.88   409.9  771.63   419.6  773.04   468.4  781.53   497.7  786.28
#Mann= 3 , 0 , 0
       0     .06       0   175.7    .045       0   195.7     .06       0
Bank Sta=175.7,195.7
XS Rating Curve= 0 ,0
Exp/Cntr=0.3,0.1

Type RM Length L Ch R = 1 ,4852.9  ,243.5,275.9,308.4
XS GIS Cut Line= 2
      1856797.63      591923.705     1857227.646      591946.487
#Sta/Elev= 30
       0  745.41     9.8  746.74    19.6  747.21    29.4  745.89    39.2   743.1
    68.5  733.55    88.1  727.49   107.6  721.63   117.4  719.15   127.2   717.6
     137  716.78   166.4   714.9   176.2  714.63     186  714.94   195.7  716.18
     200 717.114   225.1  722.78   234.9  725.13   244.7  728.41   254.5  732.71
     274  742.22   303.4  756.76     323  766.16   332.8  770.53   342.5  774.59
   362.1  782.28   381.7  789.39     411  799.55   420.8  802.86   430.6  805.98
#Mann= 3 , 0 , 0
       0     .06       0   176.2    .045       0     200     .06       0
Bank Sta=176.2,200
XS Rating Curve= 0 ,0
Exp/Cntr=0.3,0.1

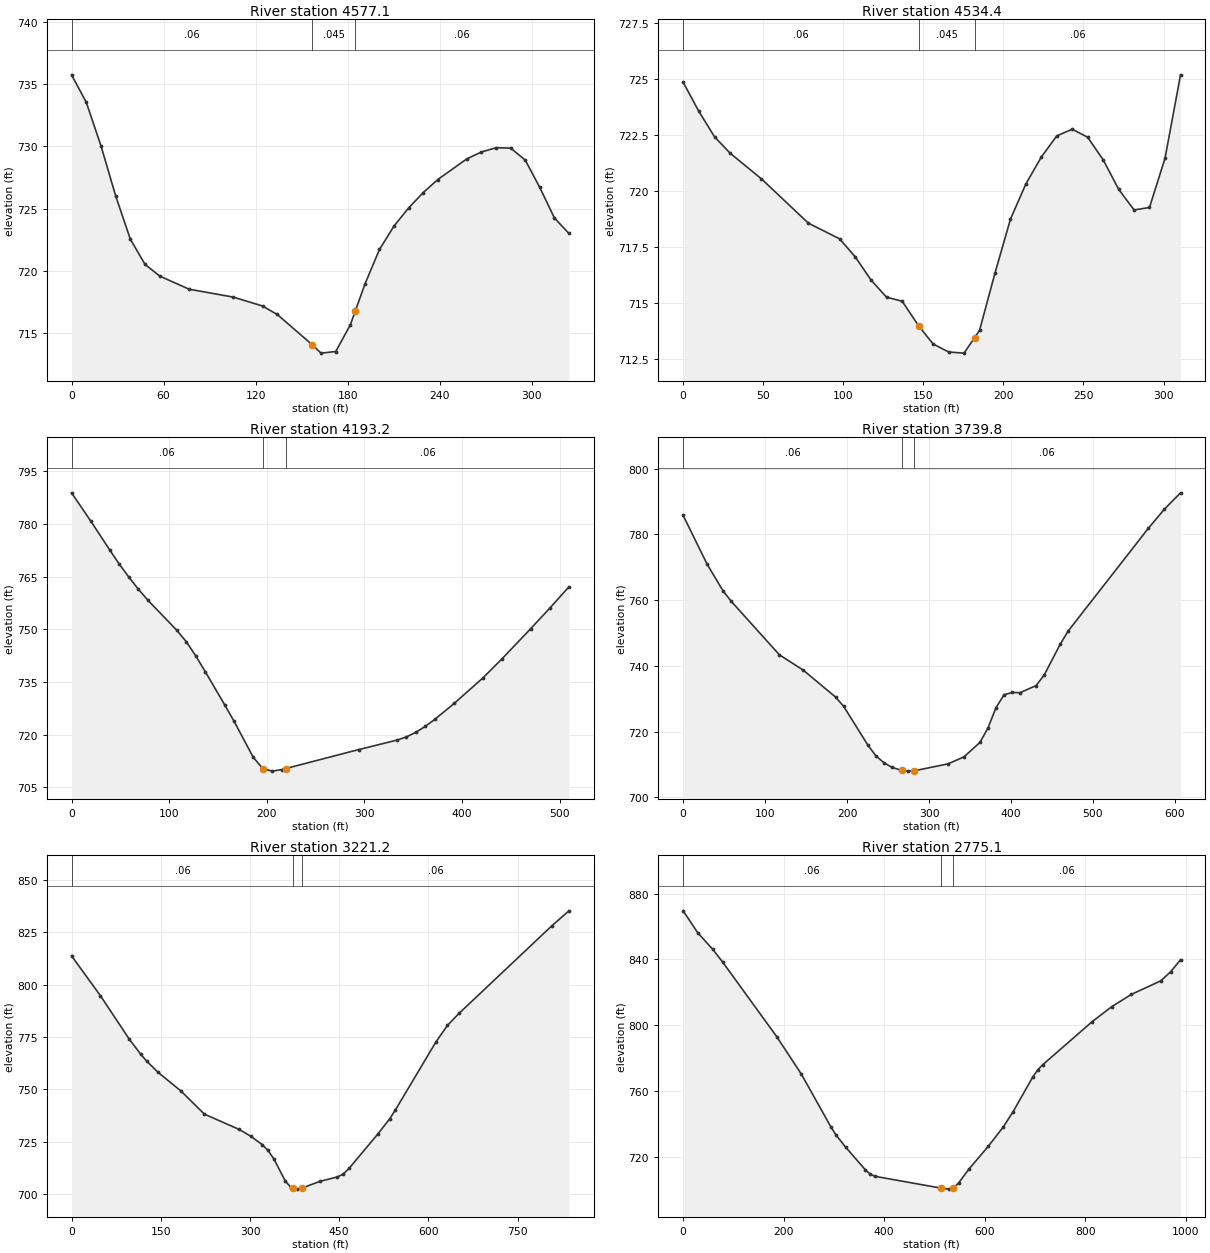
Type RM Length L Ch R = 1 ,4577.1  ,42.3,42.5,43.4
XS GIS Cut Line= 3
     1856801.668      591981.081     1856860.008      592112.348
     1856874.521      592292.309
#Sta/Elev= 30
       0  735.73     9.6  733.53    19.2  730.03    28.7  726.04    38.3  722.55
    47.9  720.52    57.5  719.58    76.6  718.53   105.3   717.9   124.5  717.18
   134.1   716.5     157 714.061   162.6   713.4   172.2  713.53   181.7  715.67
     185 716.802   191.2  718.93   200.7  721.72   210.2   723.6   219.7  725.05
   229.2  726.28   238.7  727.33   257.7  728.99   267.2  729.54   276.7  729.88
   286.2  729.85   295.7  728.89   305.2  726.69   314.7  724.25   324.2     723
#Mann= 3 , 0 , 0
       0     .06       0     157    .045       0     185     .06       0
Bank Sta=157,185
XS Rating Curve= 0 ,0
Exp/Cntr=0.3,0.1

Type RM Length L Ch R = 1 ,4534.4  ,364.2,340,314.9
XS GIS Cut Line= 3
     1856765.115      591997.327     1856820.686      592122.361
     1856834.651      592295.524
#Sta/Elev= 30
       0  724.86     9.8  723.56    19.6  722.42    29.3  721.69    48.9  720.54
    78.2  718.56    97.7  717.86   107.5  717.05   117.3  716.02     127  715.25
   136.8  715.07     147 713.975   156.1  713.16   165.8   712.8   175.4  712.75
     182  713.44   185.1  713.77   194.7  716.32   204.4  718.74     214  720.31
   223.7  721.52   233.3  722.46     243  722.76   252.6   722.4   262.3  721.39
     272  720.07   281.6  719.15   291.2  719.26   300.9  721.46   310.6  725.19
#Mann= 3 , 0 , 0
       0     .06       0     147    .045       0     182     .06       0
Bank Sta=147,182
XS Rating Curve= 0 ,0
Exp/Cntr=0.3,0.1

Type RM Length L Ch R = 1 ,4193.2  ,455.2,453.4,452.1
XS GIS Cut Line= 2
     1856393.245      592288.696     1856853.953      592506.393
#Sta/Elev= 30
       0  788.86    19.6  780.87    39.2  772.56      49  768.52    58.8  764.84
    68.6  761.37    78.4  758.24   107.8  749.74   117.6  746.47   127.4  742.37
   137.2  737.86   156.8  728.56   166.6  723.77   186.2  713.56     196  710.34
   205.8  709.63   215.6  710.08   219.5  710.37     294  715.75   333.2  718.45
     343  719.36   352.8  720.68   362.6  722.41   372.4  724.42     392   728.9
   421.4  736.15     441   741.6   470.4  750.19     490  756.03   509.6  762.12
#Mann= 3 , 0 , 0
       0     .06       0     196    .045       0   219.5     .06       0
Bank Sta=196,219.5
XS Rating Curve= 0 ,0
Exp/Cntr=0.3,0.1

Type RM Length L Ch R = 1 ,3739.8  ,517.4,518.4,519.2
XS GIS Cut Line= 2
     1856299.304       592690.62     1856851.328      592942.631
#Sta/Elev= 30
       0  785.77    29.4  770.84    48.9  762.75    58.7  759.63   117.4  743.38
   146.8  738.66     186  730.51   195.8  727.71   225.1  716.02   234.9  712.72
   244.7  710.59   254.5  709.18   266.7  708.22     274     708   281.7  708.09
     323   710.2   342.6  712.33   362.1  716.74   371.9  721.13   381.7  727.32
   391.5   731.2   401.3  731.91   411.1  731.86   430.6  734.02   440.4  737.18
     460  746.59   469.8  750.63   567.7  781.89   587.2  787.68   606.8  792.62
#Mann= 3 , 0 , 0
       0     .06       0   266.7    .045       0   281.7     .06       0
Bank Sta=266.7,281.7
XS Rating Curve= 0 ,0
Exp/Cntr=0.3,0.1

Type RM Length L Ch R = 1 ,3221.2  ,453.8,445.4,437.1
XS GIS Cut Line= 3
     1856035.292      592990.633     1856167.298      593170.641
     1856731.323      593410.652
#Sta/Elev= 30
       0  813.82    48.5  794.76      97     774   116.5  766.71   126.2   763.5
   145.6   758.1   184.4  749.09   223.2  738.17   281.6  730.86   301.1  727.62
   320.5  723.59   330.2   720.8     340  716.82   359.4  706.16   369.2  702.98
   372.9  702.72   378.9   702.3   387.9  702.86   417.8  706.04     447  708.12
   456.7  709.51   466.5  712.19   515.1  728.71   534.6   735.8   544.3  740.08
   612.4  772.57   631.9  780.54   651.3  786.27     807  828.05   836.2  835.31
#Mann= 3 , 0 , 0
       0     .06       0   372.9    .045       0   387.9     .06       0
Bank Sta=372.9,387.9
XS Rating Curve= 0 ,0
Exp/Cntr=0.3,0.1

Type RM Length L Ch R = 1 ,2775.1  ,724.9,731.3,736.5
XS GIS Cut Line= 2
     1855763.857      593660.938     1856753.535      593673.156
#Sta/Elev= 30
       0  869.51    29.4  856.07    58.8  846.19    78.4   838.5   186.2  793.12
   235.2  770.37     294   738.3   303.8  733.58   323.4  725.96   362.6  712.23
   372.4  709.52   382.2  708.24     514 701.069   529.2  700.49   536.2  701.15
     539  701.42   548.8  704.47   568.4  712.54   607.6  726.65     637  738.22
   656.6  747.52   695.8   768.6   705.6  772.87   715.4  776.01   813.4  802.06
   852.6  811.25   891.8  818.74   950.6  827.01   970.2  832.55   989.8  839.81
#Mann= 3 , 0 , 0
       0     .06       0     514    .045       0   536.2     .06       0
Bank Sta=514,536.2
XS Rating Curve= 0 ,0
Exp/Cntr=0.3,0.1

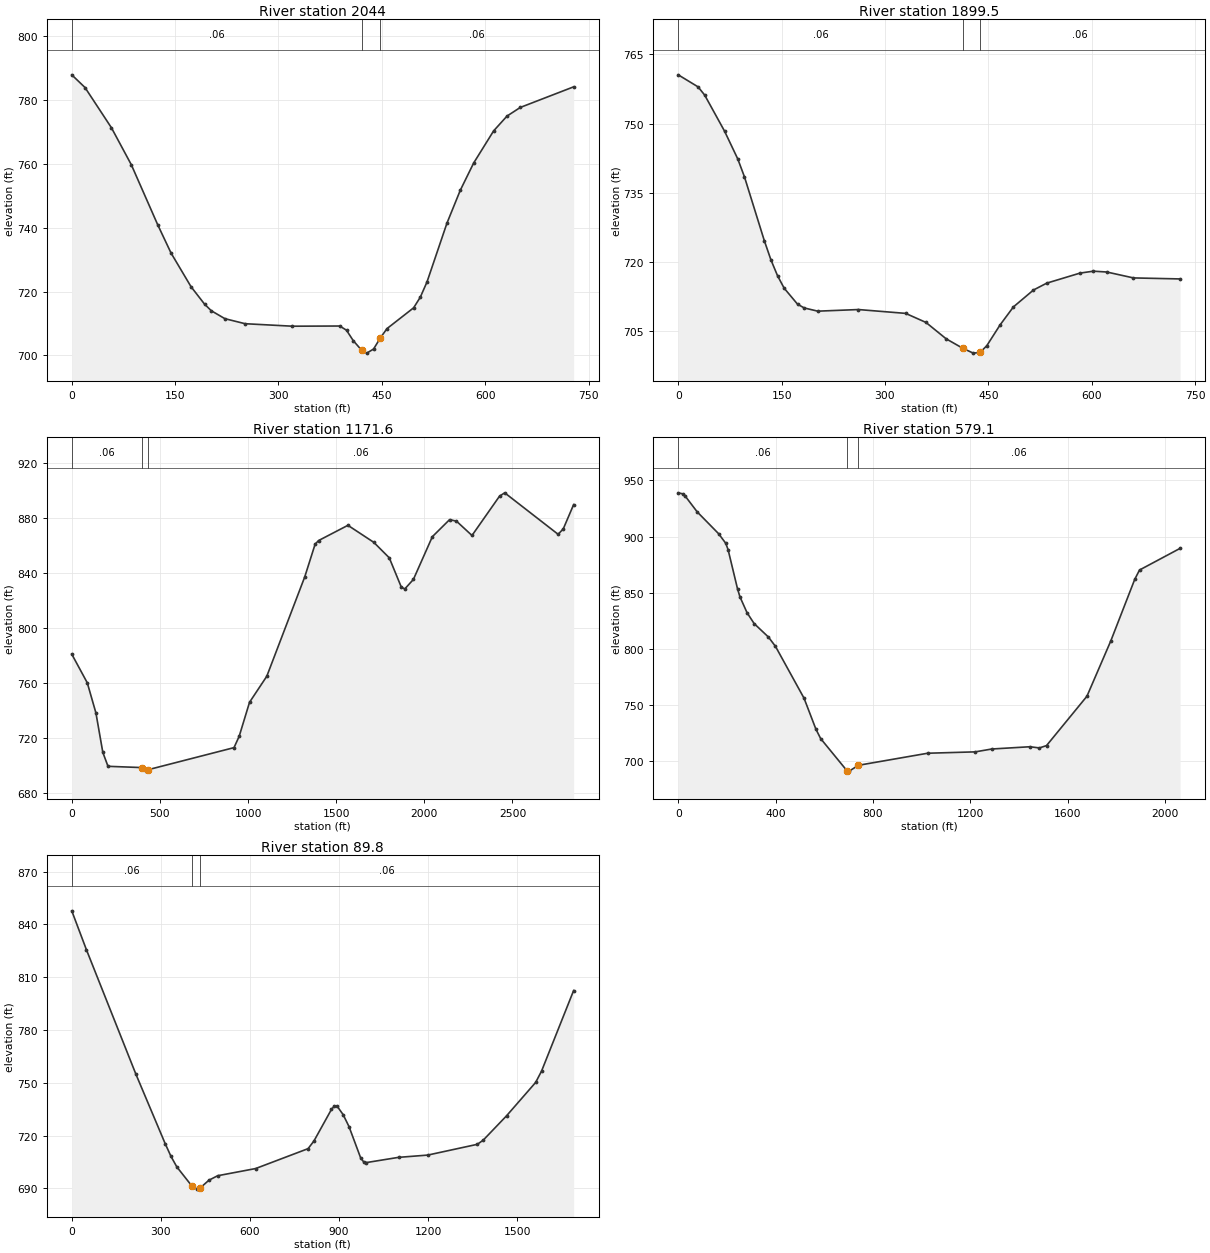
Type RM Length L Ch R = 1 ,2044    ,144.5,144.5,145
XS GIS Cut Line= 4
     1855964.288      594286.234     1856126.657      594303.631
     1856397.575      594390.342     1856678.096      594390.342
#Sta/Elev= 30
       0  787.87    19.2   783.9    57.6  771.29    86.4  759.73   124.9  740.84
   144.1  732.06   173.1  721.52   192.7  716.07   202.5     714   222.2  711.52
   251.6  709.94   320.2  709.16   388.9  709.22   398.7   707.9   408.5  704.63
     421  701.56   428.1  700.73     438  702.02   447.8  705.49   457.4   708.4
   496.1  714.92   505.8  718.25   515.5  723.01   544.5  741.45   563.8  751.72
   583.2  760.25   612.2  770.32   631.6  774.95   650.9  777.66   728.3  784.11
#Mann= 3 , 0 , 0
       0     .06       0     421    .045       0   447.8     .06       0
Bank Sta=421,447.8
XS Rating Curve= 0 ,0
Exp/Cntr=0.3,0.1

Type RM Length L Ch R = 1 ,1899.5  ,703.4,728.1,753.4
XS GIS Cut Line= 4
     1855937.921      594428.443     1856100.291      594445.839
     1856371.208      594532.551     1856651.729      594532.551
#Sta/Elev= 30
       0  760.57    28.8  757.96    38.4  756.18    67.2  748.38    86.4  742.35
    96.1  738.48   124.9  724.66   134.5   720.5   144.1  717.06   153.7  714.36
   173.1   710.9   182.9  710.07   202.5  709.38   261.4  709.73     330   708.9
   359.5  706.94   388.9  703.38     413 701.338   428.1  700.29     438  700.44
   447.8   701.9   467.1  706.41   486.4   710.3   515.5  713.96   534.8  715.45
   583.2  717.63   602.5  718.04   621.9  717.86   660.6  716.58   728.3  716.36
#Mann= 3 , 0 , 0
       0     .06       0     413    .045       0     438     .06       0
Bank Sta=413,438
XS Rating Curve= 0 ,0
Exp/Cntr=0.3,0.1

Type RM Length L Ch R = 1 ,1171.6  ,597.3,592.1,587
XS GIS Cut Line= 3
      1855759.28      594370.694      1855999.29      595918.763
      1857343.35      596770.801
#Sta/Elev= 30
       0  781.34    88.1  760.46   137.1  738.54   176.2  709.88   205.6  699.74
     397 698.826     421  696.24     432  697.23   920.4  713.33   949.7  721.55
  1008.5  746.32  1106.4  765.24  1321.8  837.56  1380.5   861.3  1400.1  863.94
  1566.6  875.03  1713.2  862.67  1801.2  851.39  1869.6  830.05  1889.2  828.76
    1938  835.66  2045.6  866.76  2143.3  879.16  2182.4  878.06  2270.4  867.64
  2426.8  896.25  2456.1  898.66  2759.2  868.48  2788.5  872.51  2847.1  890.11
#Mann= 3 , 0 , 0
       0     .06       0     397    .045       0     432     .06       0
Bank Sta=397,432
XS Rating Curve= 0 ,0
Exp/Cntr=0.3,0.1

Type RM Length L Ch R = 1 ,579.1   ,487,489.2,491.8
XS GIS Cut Line= 4
     1855350.342      594056.294      1855144.62      594399.164
     1855517.967      595603.018     1855795.281      595894.762
#Sta/Elev= 30
       0     939    19.5  938.05    29.3  935.93      78  922.02   165.8  902.62
     195  894.15   204.8  888.51   243.8  853.41   253.6   846.4   282.8  832.23
   312.1   822.5   370.6  810.56   399.8  802.19   517.1  756.06     566  728.41
   585.5  720.06     693  691.59   702.7  691.09   740.7  696.29  1025.2  707.03
  1220.6  708.25    1289   710.8  1445.3  712.81  1484.4  711.76  1513.7  713.82
  1679.9  757.81  1778.1  807.18  1876.2  861.86  1895.9  870.23  2062.8  889.54
#Mann= 3 , 0 , 0
       0     .06       0     693    .045       0   740.7     .06       0
Bank Sta=693,740.7
XS Rating Curve= 0 ,0
Exp/Cntr=0.3,0.1

Type RM Length L Ch R = 1 ,89.8    ,104.5,89.8,74.8
XS GIS Cut Line= 2
      1854654.19      594326.275     1855158.446      595939.896
#Sta/Elev= 30
       0  847.75    49.1  825.76   216.2  754.84   314.5  715.49   334.2  708.19
   353.8  702.22   405.2  691.22   422.6  689.56   432.5  690.22     462  694.63
   491.4  697.17   619.2  701.25   796.1  712.57   815.8  716.93   874.8  734.88
   884.6  736.79   894.4  736.57   914.1  731.92   933.8  725.15   973.1  707.35
   982.9  705.12   992.7  704.66  1100.8  707.62  1199.1  708.91  1366.2  715.03
  1385.9  717.38  1464.5  731.22  1562.8  750.25  1582.5  756.65  1690.6  802.46
#Mann= 3 , 0 , 0
       0     .06       0   405.2    .045       0   432.5     .06       0
Bank Sta=405.2,432.5
XS Rating Curve= 0 ,0
Exp/Cntr=0.3,0.1

Chan Stop Cuts=-1
Use User Specified Reach Order=0
Composite Channel Slope=5